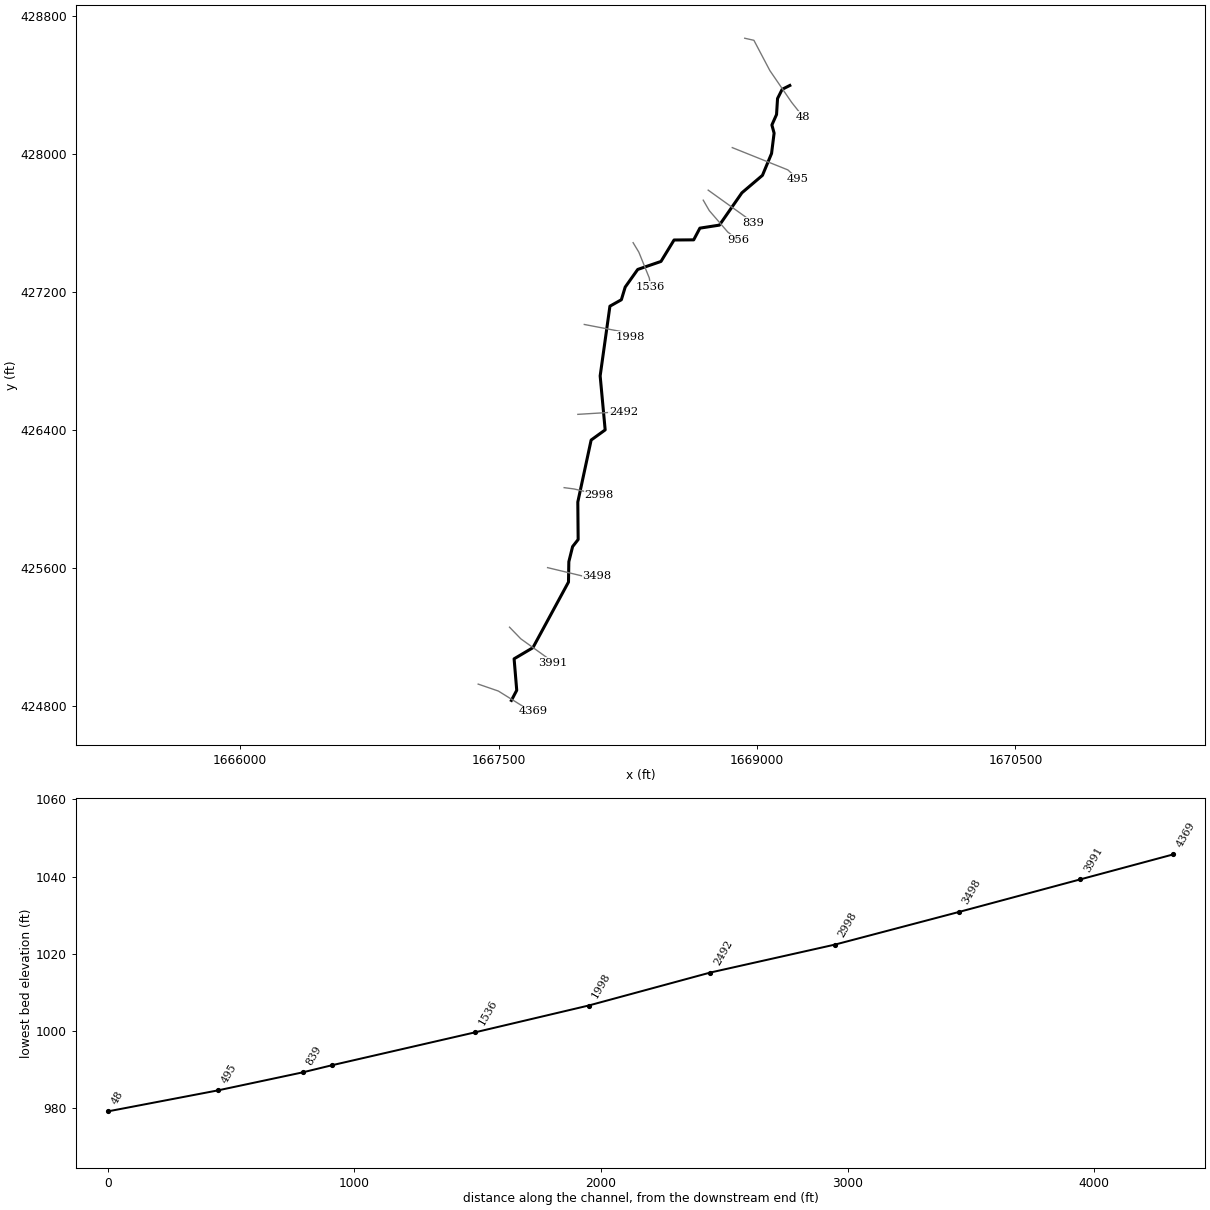
--- BEARRN.prj (project) ---

Proj Title=BEARRN
Current Plan=p01
Default Exp/Contr=0,0
English Units
Geom File=g01
Flow File=f01
Plan File=p01
BEGIN DESCRIPTION:
---------- MODELED AS PART OF WVEMD CTP PROGRAM, 2023----------
Stream Name: Bear Run
Flood Zone:  AFH
Wetzel County, WV
HEC-RAS Version: RAS 6.3
Vertical Datum: NAVD88
Projection: NAD 1983 StatePlane West Virginia S FIPS 4702 (US Feet)
Terrain: 1-meter West Virginia FEMA R3 South Central (collected 2018-2020)
Land Use: 2019 NLCD
Hydrologic Method:
WV SIR2010-5033 regression equations
Additional Model Notes:
None
END DESCRIPTION:
DSS Export Rating Curves= 0
DSS Export Rating Curve Sorted= 0
DSS Export Volume Flow Curves= 0
DXF OffsetX= 0
DXF OffsetY= 0
DXF ScaleX= 0
DXF ScaleY= 0

--- BEARRN.p01 (plan) ---

Plan Title=Floodplain
Program Version=6.30
Short Identifier=Floodplain
Geom File=g01
Flow File=f01
Subcritical Flow
K Sum by GR= 0
Std Step Tol= 0.01
Critical Tol= 0.01
Num of Std Step Trials= 20
Max Error Tol= 0.3
Flow Tol Ratio= 0.001
Split Flow NTrial= 30
Split Flow Tol= 0.02
Split Flow Ratio= 0.02
Log Output Level= 0
Friction Slope Method= 1
Unsteady Friction Slope Method= 2
Unsteady Bridges Friction Slope Method= 1
Parabolic Critical Depth
Global Vel Dist= 0 , 0 , 0
Global Log Level= 0
CheckData=False
Encroach Param=-1 ,0,0, 0
Mapping Interval=1HOUR
Computation Time Step Use Courant=        0
Computation Time Step Use Time Series=    0
Computation Time Step Count To Double=0
Computation Time Step Max Doubling=0
Computation Time Step Max Halving=0
Computation Time Step Residence Courant=0
Run HTab= 0
Run UNet= 0
Run Sediment= 0
Run PostProcess= 0
Run WQNet= 0
Run RASMapper=-1
UNET Theta= 0
UNET Theta Warmup= 0
UNET ZTol= 0
UNET ZSATol= 0
UNET MxIter= 0
UNET Max Iter WO Improvement= 0
UNET MaxInSteps= 0
UNET DtIC= 0
UNET DtMin= 0
UNET MaxCRTS= 0
UNET WFStab= 0
UNET SFStab= 0
UNET WFX= 1
UNET SFX= 1
UNET Gravity=32.17405
UNET 1D Methodology=Finite Difference
UNET DSS MLevel= 1
UNET Pardiso=0
UNET DZMax Abort= 0
UNET Use Existing IB Tables= 0
UNET Froude Reduction=False
UNET Froude Limit= 0
UNET Froude Power= 0
UNET D1 Cores= 0
UNET WindReference=Eulerian
UNET WindDragFormulation=Hsu (1988)
UNET D2 Coriolis=0
UNET D2 Cores= 0
UNET D2 Theta= 1
UNET D2 Theta Warmup= 1
UNET D2 Z Tol= 0.01
UNET D2 Volume Tol= 0.01
UNET D2 Max Iterations= 20
UNET D2 Equation= 0
UNET D2 RampUpFraction=0.1
UNET D2 TimeSlices= 1
UNET D2 Turbulence Formulation=Non-Conservative (original)
UNET D2 Eddy Viscosity=0.3
UNET D2 Transverse Eddy Viscosity=0.1
UNET D2 Smagorinsky Mixing=0
UNET D2 BCVolumeCheck=0
UNET D2 Cores=0
UNET D2 SolverType=PARDISO (Direct)
UNET D2 Minimum Iterations= 3
UNET D2 Maximum Iterations= 30
UNET D2 Restart Number= 10
UNET D2 Relaxation Coeff=1.3
UNET D2 SOR Precondition Iterations= 10
UNET D2 ILUT Maximum Fill= 8
UNET D2 ILUT Tolerance=1E-08
UNET D2 Convergence Tolerance=0.00001
UNET D1D2 MaxIter= 0
UNET D1D2 ZTol=0.01
UNET D1D2 QTol=0.1
UNET D1D2 MinQTol=1
Write IC File= 0
Write IC File at Fixed DateTime=0
Write IC File at Sim End=0
Echo Input=False
Echo Parameters=False
Echo Output=False
Write Detailed= 0
HDF Write Warmup=0
HDF Write Time Slices=0
HDF Flush=0
HDF Compression= 1
HDF Chunk Size= 1
HDF Spatial Parts= 1
HDF Use Max Rows=0
HDF Fixed Rows= 1
Calibration Method= 0
Calibration Iterations= 20
Calibration Max Change=0.05
Calibration Tolerance=0.2
Calibration Maximum=1.5
Calibration Minimum=0.5
Calibration Optimization Method= 1
WQ AD Non Conservative
WQ ULTIMATE=-1
WQ Max Comp Step=1HOUR
WQ Output Interval=15MIN
WQ Output Selected Increments= 0
WQ Output face flow=0
WQ Output face velocity=0
WQ Output face area=0
WQ Output face dispersion=0
WQ Output cell volume=0
WQ Output cell surface area=0
WQ Output cell continuity=0
WQ Output cumulative cell continuity=0
WQ Output face conc=0
WQ Output face dconc_dx=0
WQ Output face courant=0
WQ Output face peclet=0
WQ Output face adv mass=0
WQ Output face disp mass=0
WQ Output cell mass=0
WQ Output cell source sink temp=0
WQ Output nsm pathways=0
WQ Output nsm derived pathways=0
WQ Create Restart=0
WQ Fixed Restart=0
WQ System Summary=0
WQ Write To DSS=0
Sorting and Armoring Iterations= 10
XS Update Threshold= 0.02
Bed Roughness Predictor= 0
Hydraulics Update Threshold= 0.02
Energy Slope Method= 1
Volume Change Method= 1
Sediment Retention Method= 0
Sediment TS Multiplier= 1
Warm Up Method= 0
XS Weighting Method= 0
Number of US Weighted Cross Sections= 1
Number of DS Weighted Cross Sections= 1
Upstream XS Weight=0
Main XS Weight=1
Downstream XS Weight=0
Number of DS XS's Weighted with US Boundary= 1
Upstream Boundary Weight= 1
Weight of XSs Associated with US Boundary= 0
Number of US XS's Weighted with DS Boundary= 1
Downstream Boundary Weight= 0.5
Weight of XSs Associated with DS Boundary= 0.5
Percentile Method= 0
Sediment Output Level= 3
Mass or Volume Output= 0
Output Increment Type= 1
Profile and TS Output Increment= 1
Transport Output Increment 1
XS Output Flag= 0
XS Output Increment= 10
Read HDF5 Sediment Hotstart= 0
Sediment Hotstart Type= 0
Write Gradation File= 0
Read Gradation Hotstart= 0
Write HDF5 File= 1
Write Binary Output= 1
Write DSS Sediment File= 0
DSS Sediment Output Type= 1
SV Curve= 0
Specific Gage Flag= 0
Subcell Erosion Methods= 0
Subcell Deposition Methods= 0
Advection Scheme= 1
Matrix Solver= 0
Implicit Weighting Factor= 1
Maximum Outer Loop Convergence Iterations= 5
Convergence Maximum Absolute= 0.001
Convergence RMSE= 0.0001
Grain Fractions Max Abs Error= 0.001
Max Subgrid Regions= 1
Max Subgrid Length Scale= 3.402823E+38
Initial Layer Thickness= 3.402823E+38
Min Layer Thickness= 3.402823E+38
Max Layer Thickness= 3.402823E+38
Number of Layers= 5

--- BEARRN.f01 (steady flow) ---

Flow Title=Flow
Program Version=6.30
Number of Profiles= 1
Profile Names=F01pct
River Rch & RM=BEARRN,Main,4369
     734
Boundary for River Rch & Prof#=BEARRN,Main            , 1
Up Type= 0
Dn Type= 3
Dn Slope=0.01032
DSS Import GetInterval= 0
DSS Import GetPeak= 0
DSS Import FillOption= 0

--- BEARRN.g01 (geometry) ---

Geom Title=Geometry
Program Version=6.31

River Reach=BEARRN          ,Main
Reach XY= 30
1667574.77483507424829.5220213741667605.73489182424888.495627505
1667590.48590571425070.928849258     1667699.588      425135.473
     1667906.104       425516.29     1667908.117      425634.216
     1667929.977      425721.942     1667962.191      425763.072
     1667960.177      425980.517     1668037.549       426340.05
     1668118.947      426399.013     1668089.897      426712.237
     1668146.559      427116.639        1668213.       427154.03
     1668235.147      427227.375     1668307.917      427329.769
     1668442.905      427376.215     1668518.746      427500.619
     1668632.646      427501.482     1668668.599      427569.361
     1668781.924      427586.907     1668912.332      427774.285
     1669031.779      427875.809     1669084.506      428002.274
     1669099.337       428120.47     1669086.519       428167.91
     1669113.501      428228.553     1669119.309      428321.215
     1669146.073      428374.603     1669190.468       428397.06

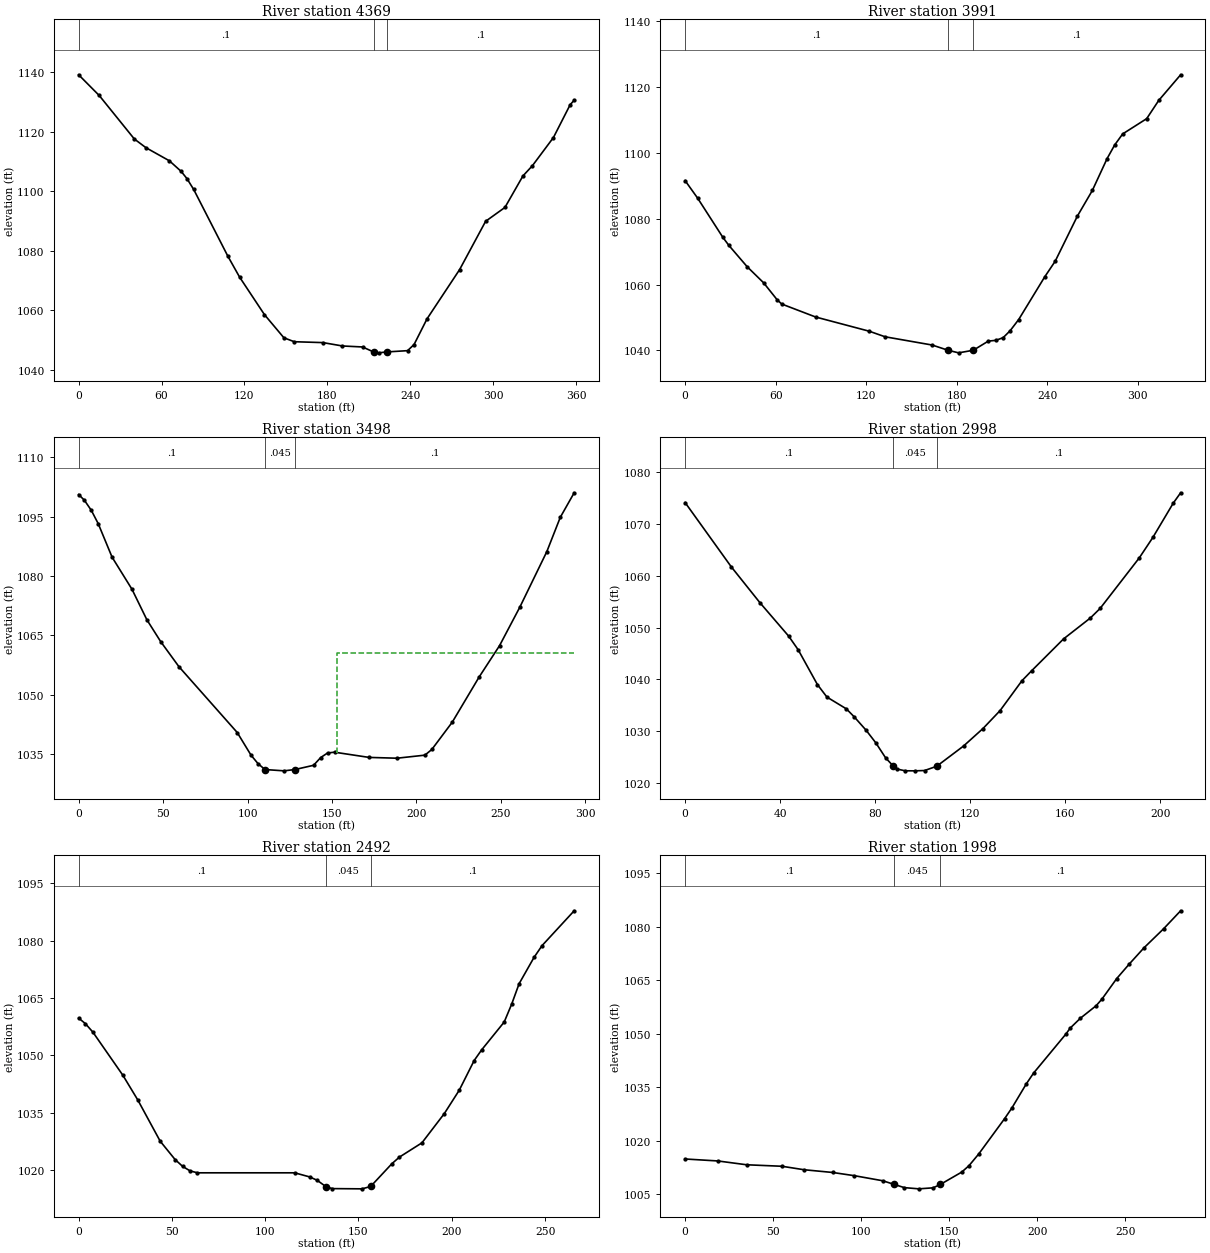
Type RM Length L Ch R = 1 ,4369    ,378.1,378.2,374.4
XS GIS Cut Line= 4
1667382.00523172424924.2798543221667499.12811341424883.937528406
1667653.99059031 424787.636492351667702.14110834424766.814646717
#Sta/Elev= 30
       0 1139.03    14.9 1132.08    40.3  1117.5    48.7 1114.58    65.7 1110.17
    74.2 1106.63    78.4 1104.21    83.3 1100.55     108 1078.19   116.5 1071.17
   134.5 1058.58   148.6  1050.8   156.1 1049.49   176.9 1049.19     191 1048.06
   205.5 1047.73   213.6 1046.04   217.1 1045.76   222.9 1046.06   238.1 1046.49
   242.8 1048.54   252.2 1057.17   275.8  1073.7   294.6 1089.88   308.6 1094.54
   321.6 1105.09   328.5 1108.55   343.7 1117.99   355.8 1128.99   358.7 1130.49
#Mann= 3 ,-1,0
       0      .1       0   213.6    .045       0   222.9      .1       0
Bank Sta=213.6,222.9
XS Rating Curve= 0 ,0
Exp/Cntr(USF)=0,0
Exp/Cntr=0.3,0.1

Type RM Length L Ch R = 1 ,3991    ,487.7,493.3,494.9
XS GIS Cut Line= 4
1667563.91061465425254.5097177641667629.26518263425187.046937911
1667786.32696698425074.257602844 1667816.8960391425046.850848528
#Sta/Elev= 30
       0 1091.62     8.3 1086.29      25 1074.38      29 1071.92    41.1 1065.45
      52 1060.56    60.9 1055.44      64  1054.1    86.5 1050.15   122.1 1045.82
   132.5 1044.14   163.7 1041.63   174.31040.032   181.2 1039.26   190.91040.043
   200.9 1042.83   205.8 1043.05   210.7 1043.87   215.3 1045.96     221 1049.38
   238.2 1062.32   245.2 1067.12   259.9 1080.84   269.8 1088.62   279.6 1098.33
   284.6 1102.45   289.9 1105.81   305.8 1110.45   313.8    1116   328.3 1123.79
#Mann= 3 ,-1,0
       0      .1       0   174.3    .045       0   190.9      .1       0
Bank Sta=174.3,190.9
XS Rating Curve= 0 ,0
Exp/Cntr(USF)=0,0
Exp/Cntr=0.3,0.1

Type RM Length L Ch R = 1 ,3498    ,495.8,500,497.7
XS GIS Cut Line= 3
 1667784.8285308425599.9084580981667993.34035738 425549.80727168
1668072.32786821425550.367466792
#Sta/Elev= 30
       0 1100.58     3.4 1099.14     7.5 1096.59    11.6 1093.22    19.8 1084.76
    31.6 1076.64    40.4 1068.95    48.6 1063.42    59.4 1057.09    93.9 1040.47
   102.1 1034.73   106.2 1032.62   110.3 1031.12   121.6 1030.79   128.11031.121
   139.1 1032.19   143.3 1034.14   147.4  1035.3   151.5  1035.5     172 1034.18
   188.5 1033.98     205 1034.75   209.1 1036.18   221.2 1043.07   237.2 1054.54
   249.2  1062.4   261.2 1072.11   277.2 1086.15   285.2 1094.84   293.4 1101.02
#Mann= 3 ,-1,0
       0      .1       0   110.3    .045       0   128.1      .1       0
#XS Ineff= 2 , 0
                          152.91         1060.53
Permanent Ineff=
       F       F
Bank Sta=110.3,128.1
XS Rating Curve= 0 ,0
Exp/Cntr(USF)=0,0
Exp/Cntr=0.3,0.1

Type RM Length L Ch R = 1 ,2998    ,498.1,506.1,506.5
XS GIS Cut Line= 4
1667880.92320118426063.8926883051667938.32591022 426056.28510036
1668040.68254803426032.7707376211668084.94487789426021.705155156
#Sta/Elev= 30
       0 1074.12    19.4 1061.74    31.5  1054.8    43.6 1048.35    47.6 1045.72
    55.7 1039.01    59.7  1036.6    67.9 1034.32    71.3 1032.73    76.2  1030.2
    80.3 1027.76    84.4 1024.88    87.7 1023.26    89.2 1022.72    92.6 1022.38
    96.7 1022.37   100.8 1022.43   105.9 1023.25   117.2 1027.15   125.4 1030.53
   132.6 1033.99   141.8 1039.75   145.9 1041.68   159.3 1047.81   170.6 1051.85
   174.7 1053.69   191.2 1063.45   196.9 1067.38   205.5 1074.01   208.6    1076
#Mann= 3 ,-1,0
       0      .1       0    87.7    .045       0   105.9      .1       0
Bank Sta=87.7,105.9
XS Rating Curve= 0 ,0
Exp/Cntr(USF)=0,0
Exp/Cntr=0.3,0.1

Type RM Length L Ch R = 1 ,2492    ,496.2,493.8,490.1
XS GIS Cut Line= 2
1667960.48556072426489.1430969561668225.59847396426505.280404719
#Sta/Elev= 30
       0 1059.77     3.6 1058.32     7.6 1056.12    23.7 1044.82    31.7 1038.36
    43.7 1027.58    51.7 1022.77    55.7    1021    59.7 1019.81    63.7  1019.3
   115.8  1019.3   123.9 1018.22   127.9 1017.33   132.5  1015.7   135.9 1015.17
   151.9 1015.11   156.51015.722   167.9 1021.68   171.9  1023.4     184 1027.14
     196 1034.79     204  1040.9     212 1048.67     216 1051.45   228.1 1058.74
   232.1 1063.41   236.1 1068.77   244.1 1075.65   248.4 1078.73   265.6 1087.83
#Mann= 3 ,-1,0
       0      .1       0   132.5    .045       0   156.5      .1       0
Bank Sta=132.5,156.5
XS Rating Curve= 0 ,0
Exp/Cntr(USF)=0,0
Exp/Cntr=0.3,0.1

Type RM Length L Ch R = 1 ,1998    ,469.6,461.5,452.7
XS GIS Cut Line= 3
1667997.80904848427010.5925804281668210.31680502426969.798680736
1668267.23852552 426938.49173446
#Sta/Elev= 30
       0 1014.92    18.6 1014.37    34.9  1013.3      55 1012.88    67.5 1011.91
    83.8 1011.14    96.1 1010.24   112.3 1008.81   118.41007.844   124.5 1006.89
   132.7 1006.55   140.8 1006.83   144.9 1007.77   157.1 1011.25   161.2 1013.04
   166.7  1016.3   181.4 1026.21   185.6 1029.25   193.8 1036.02   197.9 1039.02
   216.4 1050.05   218.6 1051.59   224.5 1054.41   233.4  1057.9   236.7 1059.75
   245.1 1065.52   252.2 1069.58   260.5  1074.1   271.7 1079.47   281.4 1084.53
#Mann= 3 ,-1,0
       0      .1       0   118.4    .045       0   144.9      .1       0
Bank Sta=118.4,144.9
XS Rating Curve= 0 ,0
Exp/Cntr(USF)=0,0
Exp/Cntr=0.3,0.1

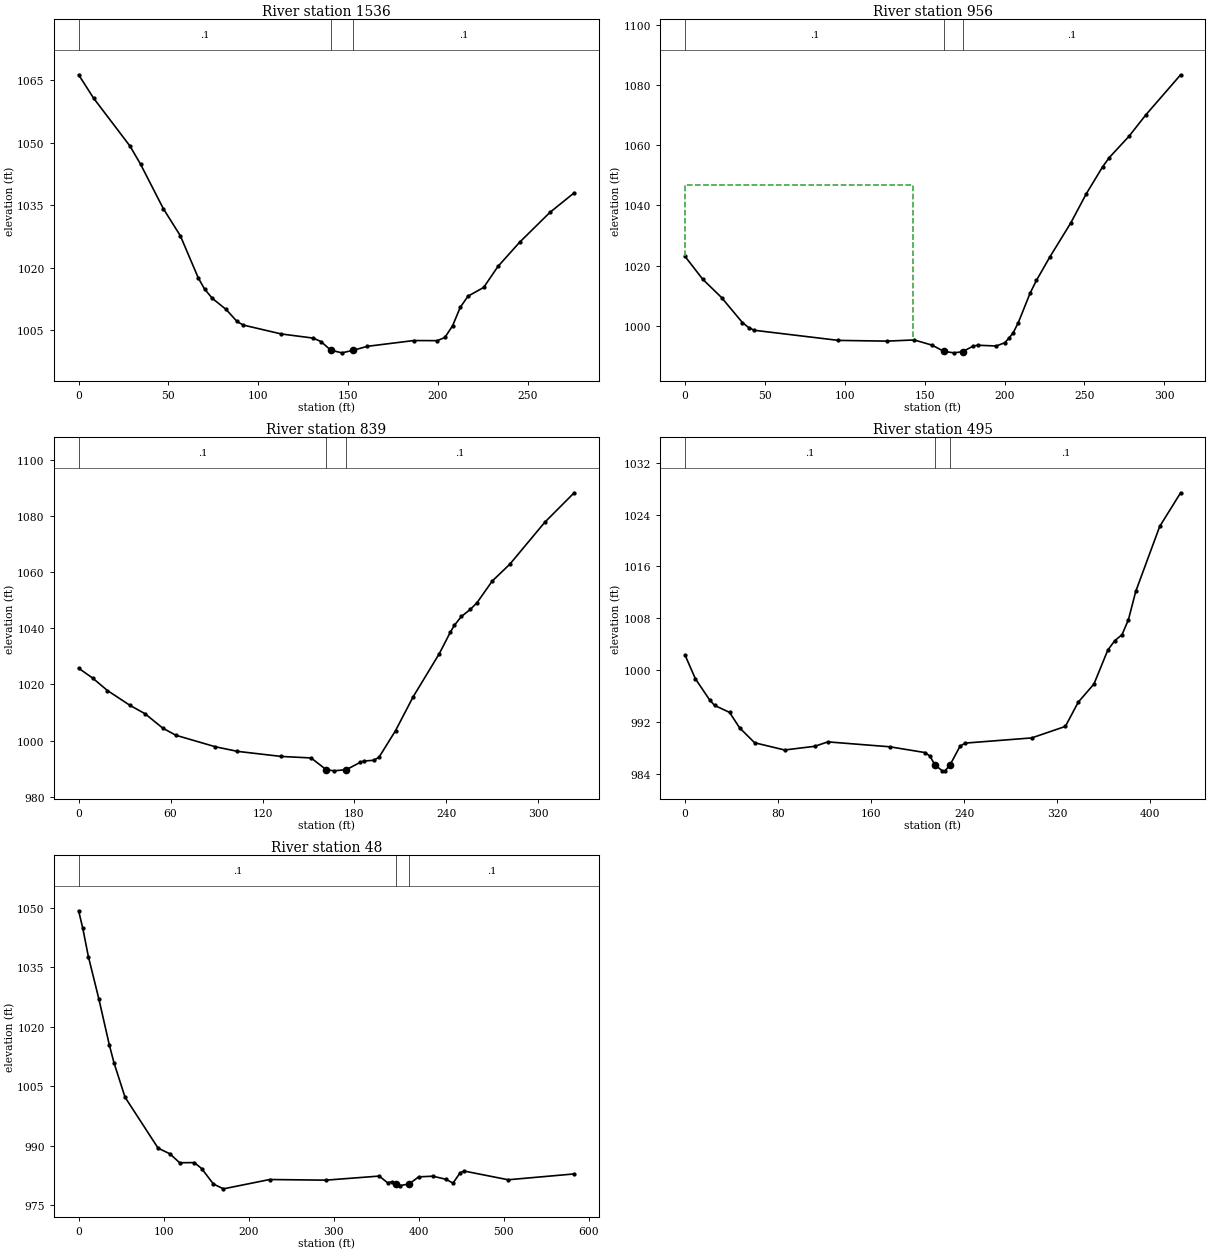
Type RM Length L Ch R = 1 ,1536    ,573.3,580.1,579.7
XS GIS Cut Line= 4
1668281.14708052427484.9821427091668314.35141748427429.957812891
1668375.06791935427280.0639489041668382.65748208427230.731791136
#Sta/Elev= 30
       0 1066.28     8.3 1060.69    28.6 1049.17    34.5 1044.81    47.2 1034.13
    56.6 1027.69    66.7 1017.47    70.1  1014.9    74.4 1012.66    82.1 1009.99
    88.2  1007.1    91.7 1006.24   112.8 1004.11   130.5 1003.12   134.9  1002.3
   140.4 1000.21   146.6  999.58   152.91000.194   160.7 1001.14   186.6 1002.53
   199.6  1002.5   203.9 1003.26   208.2 1006.07   212.5 1010.51   216.8 1013.18
   225.5 1015.26   233.5 1020.32   245.7 1026.18   262.4 1033.27   275.9 1037.96
#Mann= 3 ,-1,0
       0      .1       0   140.4    .045       0   152.9      .1       0
Bank Sta=140.4,152.9
XS Rating Curve= 0 ,0
Exp/Cntr(USF)=0,0
Exp/Cntr=0.3,0.1

Type RM Length L Ch R = 1 ,956     ,115,117.5,117.8
XS GIS Cut Line= 4
1668688.13738211427731.6429315481668723.23910975 427670.92642968
1668830.44168336427546.6473399181668891.15818523427501.109963517
#Sta/Elev= 30
       0 1023.05      11 1015.51    22.8 1009.42    35.9 1001.09    39.9   999.4
    43.2  998.55      96  995.18   126.3  994.94   143.4  995.33   154.7  993.59
     162 991.517   168.4  991.05   173.7  991.44   180.2  993.25   183.1  993.58
   194.8  993.32   200.1  994.41   202.9  996.03   205.4  997.73   208.6  1001.1
   215.9 1010.79   219.9 1015.08   228.4 1022.95   241.4 1034.16   251.2 1043.93
   261.4 1052.85   265.5 1055.87   277.8 1062.91   288.4 1070.06   310.2 1083.38
#Mann= 3 ,-1,0
       0      .1       0     162    .045       0   173.7      .1       0
#XS Ineff= 2 , 0
          142.42 1046.75
Permanent Ineff=
       F       F
Bank Sta=162,173.7
XS Rating Curve= 0 ,0
Exp/Cntr(USF)=0,0
Exp/Cntr=0.3,0.1

Type RM Length L Ch R = 1 ,839     ,341.4,344.2,344.8
XS GIS Cut Line= 2
1668716.80797564427789.8153626111668979.66368626427601.439987371
#Sta/Elev= 30
       0 1025.75     9.1 1022.26    18.8 1017.81    33.6  1012.5    43.4 1009.53
    54.9 1004.42    63.5 1001.88    89.3  997.78   103.6  996.16   132.3  994.34
   151.7  993.81   161.5  989.67   166.5  989.22  174.75  989.65   183.9  992.27
   186.1   992.7   192.5  992.98     196  994.03   206.8 1003.51   218.3 1015.56
   235.4 1030.95   242.5  1038.5   245.2 1041.01   249.8 1044.16   255.6 1046.68
     260 1049.07   269.9 1056.76   281.4 1062.77   304.3 1077.75   323.4  1088.2
#Mann= 3 ,-1,0
       0      .1       0   161.5    .045       0  174.75      .1       0
Bank Sta=161.5,174.75
XS Rating Curve= 0 ,0
Exp/Cntr(USF)=0,0
Exp/Cntr=0.3,0.1

Type RM Length L Ch R = 1 ,495     ,449.6,446.4,441.4
XS GIS Cut Line= 3
1668856.62464046428036.5185582611669178.95498839427907.381633009
1669237.51642924427854.676336248
#Sta/Elev= 30
       0 1002.34     8.8  998.73      21  995.48    25.3  994.62    38.2  993.54
    46.9  991.15    59.8  988.86    85.6  987.75   111.5  988.32   122.7     989
   176.1  988.24   206.3  987.35   210.6  986.79   214.6  985.48   221.1  984.54
   223.5  984.54   227.8  985.47   236.4  988.34   240.8  988.81     298  989.61
   326.9  991.38     338  995.12   351.5  997.91   363.4 1003.14   369.4 1004.58
   375.6  1005.5   381.1  1007.8   387.4 1012.16     408 1022.17     426 1027.35
#Mann= 3 ,-1,0
       0      .1       0   214.6    .045       0   227.8      .1       0
Bank Sta=214.6,227.8
XS Rating Curve= 0 ,0
Exp/Cntr(USF)=0,0
Exp/Cntr=0.3,0.1

Type RM Length L Ch R = 1 ,48      ,,,
XS GIS Cut Line= 5
1668928.85669206428671.0846649481668982.11031529428659.088560048
 1669074.7449535428483.3483978841669201.23766573428298.879859222
1669267.19942448428215.746653076
#Sta/Elev= 30
       0 1049.22     4.9 1044.78    11.5 1037.63    23.8 1026.98    36.1 1015.39
    41.7 1010.81    54.6  1002.2    93.5  989.35   107.2  987.94   118.9  985.67
   136.1  985.71   144.7  984.21   158.6   980.3   170.4  979.09   224.8  981.44
     291  981.28   353.7  982.31   363.4  980.62   368.5  980.86   373.4980.3054
   377.9  979.92   388.6980.2961   400.1  982.11   416.7  982.28   432.5  981.48
   440.4  980.52     449  983.18   453.7  983.57   505.4  981.38     583  982.85
#Mann= 3 ,-1,0
       0      .1       0   373.4    .045       0   388.6      .1       0
Bank Sta=373.4,388.6
XS Rating Curve= 0 ,0
Exp/Cntr(USF)=0,0
Exp/Cntr=0.3,0.1
LCMann Table=0

Chan Stop Cuts=-1
Use User Specified Reach Order=0
Composite Channel Slope=5